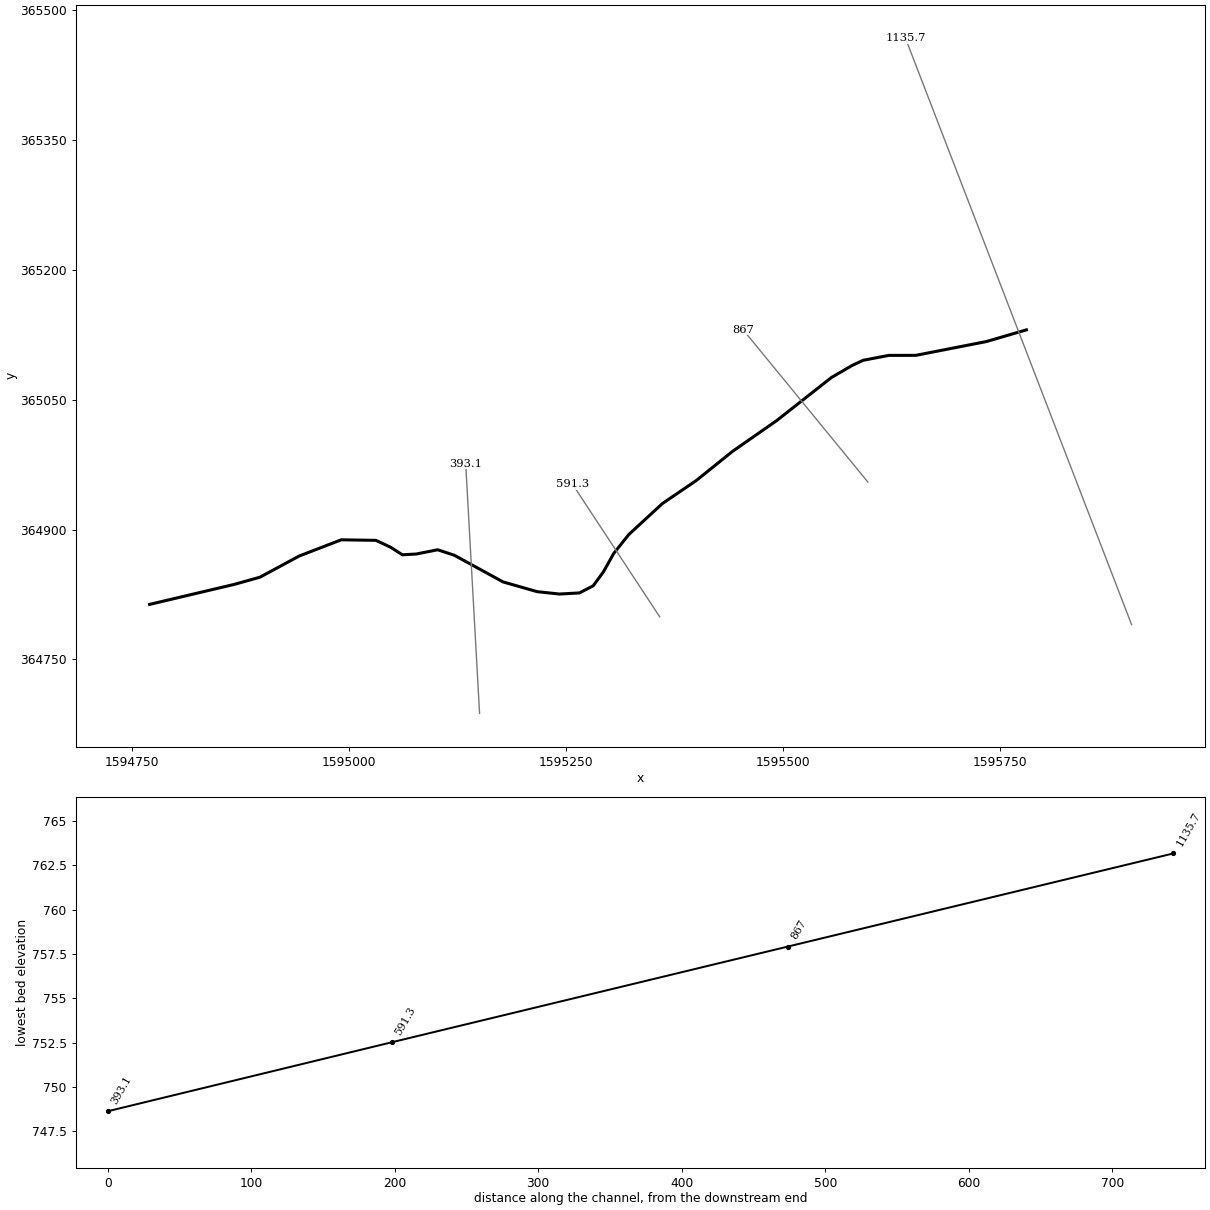
--- BLUWATRBR.prj (project) ---

Proj Title=BLUWATRBR
Current Plan=p01
Geom File=g01
Flow File=f01
Plan File=p01
DSS Export Rating Curves=0
DSS Export Rating Curve Sorted=0
DSS Export Volume Flow Curves=0
DXF OffsetX=0
DXF OffsetY=0
DXF ScaleX=0
DXF ScaleY=0

--- BLUWATRBR.p01 (plan) ---

Plan Title=Floodplain
Program Version=4.00
Geom File=g01
Flow File=f01
K Sum by GR=0
Std Step Tol=0.01
Critical Tol=0.01
Num of Std Step Trials=20
Max Error Tol=0.3
Flow Tol Ratio=0.001
Split Flow NTrial=30
Split Flow Tol=0.02
Split Flow Ratio=0.02
Log Output Level=0
Friction Slope Method=1
Unsteady Friction Slope Method=2
Unsteady Bridges Friction Slope Method=1
Global Log Level=0
CheckData=False
Run HTab=0
Run UNet=0
Run PostProcess=0
UNET Theta=0
UNET Theta Warmup=0
UNET ZTol=0
UNET ZSATol=0
UNET MxIter=0
UNET MaxInSteps=0
UNET DtIC=0
UNET DtMin=0
UNET MaxCRTS=0
UNET WFStab=0
UNET SFStab=0
UNET WFX=0
UNET SFX=0
UNET DSS MLevel=0
UNET DZMax Abort=0
UNET Convert EG Bridges=0
UNET Use Existing IB Tables=0
UNET Froude Limit=0
UNET Froude Power=0
Write IC File=0
Echo Input=False
Echo Output=False
Write Detailed=0

--- BLUWATRBR.f01 (steady flow) ---

Flow Title=NFF Regression Equation
Program Version=4.00
Number of Profiles=1
Profile Names=P100yr
River Rch & RM=BLUWATRBR,Main      ,1135.7
362.9686
Boundary for River Rch & Prof#=BLUWATRBR,Main      ,1
Up Type=0
Dn Type=3
Dn Slope=0.019616

--- BLUWATRBR.g01 (geometry) ---

Geom Title=Geometry
Program Version=4.00

River Reach=BLUWATRBR     ,Main
Reach XY= 30
     1595780.944      365130.483     1595734.714      365116.965
     1595653.378      365101.068     1595622.264      365101.014
     1595592.764      365095.382     1595580.023      365089.394
     1595556.156      365075.503     1595492.799      365025.595
     1595442.011      364990.163     1595400.039      364956.379
     1595361.165      364929.939     1595322.402      364894.156
     1595304.994      364872.239     1595293.250      364851.219
     1595281.429      364835.023     1595265.515      364826.759
     1595242.356      364825.496     1595216.789      364828.234
     1595177.523      364839.466     1595121.236      364870.289
     1595102.048      364876.602     1595077.340      364871.697
     1595061.337      364870.822     1595047.690      364879.559
     1595030.843      364887.487     1594990.850      364888.108
     1594942.324      364869.373     1594897.052      364844.915
     1594867.562      364836.658     1594769.853      364813.537

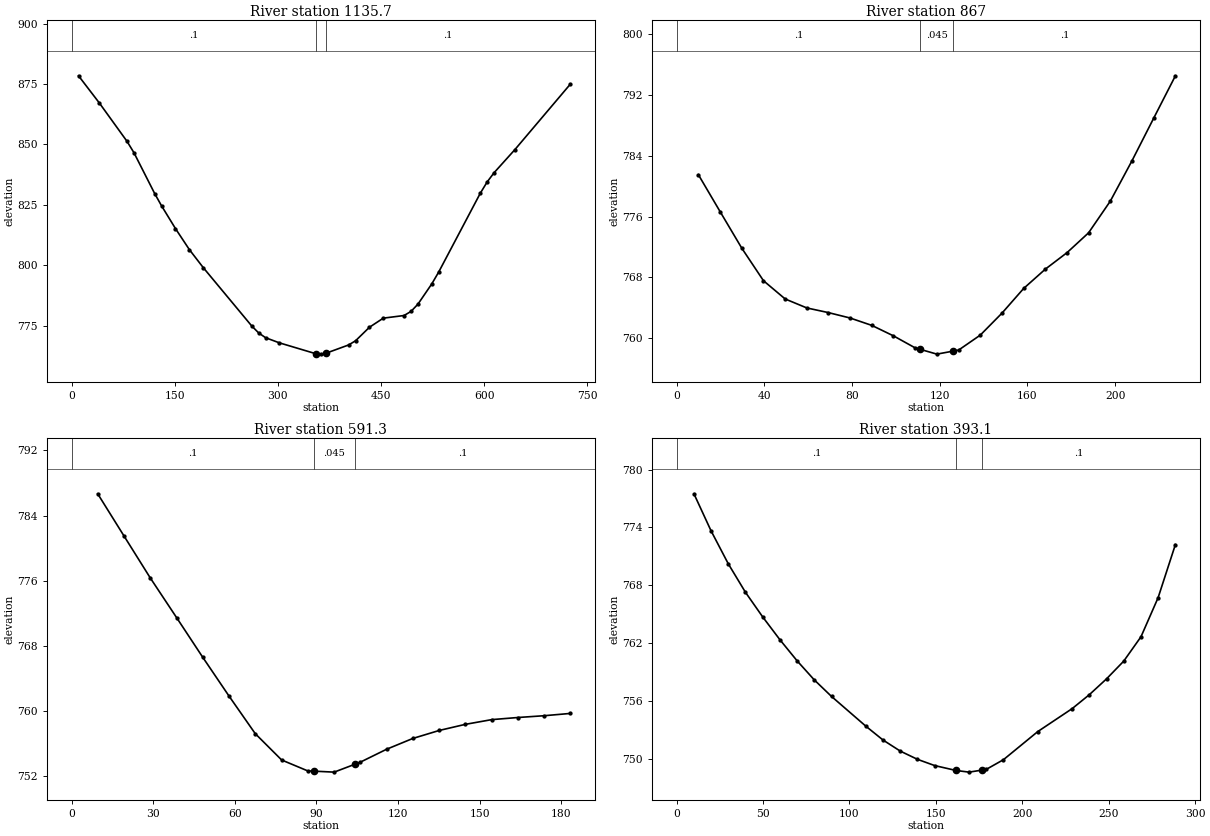
Type RM Length L Ch R = 1 ,1135.7,261.5,268.7,275.9
XS GIS Cut Line= 2
     1595902.285      364790.165     1595641.584      365467.073
#Sta/Elev= 30
    10.1  878.35    40.3  867.13    80.6  851.24    90.7  846.53   120.9  829.60
   131.0  824.47   151.1  815.13   171.3  806.43   191.4  799.01   261.9  774.87
   272.0  771.98   282.1  769.98   302.2  767.85   355.2  763.35   362.7  763.18
   370.2  763.57   403.0  766.98   413.1  768.72   433.2  774.30   453.4  778.07
   483.6  779.16   493.7  780.86   503.7  783.84   523.9  792.24   534.0  797.17
   594.4  829.73   604.5  834.46   614.6  838.28   644.8  847.82   725.4  874.90
#Mann= 3 , 0 , 0
       0     0.1       0   355.2   0.045       0   370.2     0.1       0
Bank Sta=   355.2,   370.2
Exp/Cntr=0.3,0.1

Type RM Length L Ch R = 1 ,867,278.7,275.8,273.2
XS GIS Cut Line= 2
     1595598.134      364954.818     1595454.063      365130.906
#Sta/Elev= 25
     9.9  781.51    19.8  776.66    29.7  771.85    39.6  767.57    49.5  765.17
    59.4  763.99    69.2  763.38    79.1  762.67    89.0  761.70    98.9  760.32
   108.8  758.74   111.2  758.54   118.7  757.92   126.2  758.32   128.6  758.45
   138.5  760.42   148.4  763.31   158.3  766.56   168.2  769.10   178.1  771.27
   187.9  773.87   197.8  778.03   207.7  783.34   217.6  788.94   227.5  794.51
#Mann= 3 , 0 , 0
       0     0.1       0   111.2   0.045       0   126.2     0.1       0
Bank Sta=   111.2,   126.2
Exp/Cntr=0.3,0.1

Type RM Length L Ch R = 1 ,591.3,208.3,198.2,187.7
XS GIS Cut Line= 2
     1595358.015      364799.312     1595257.394      364952.532
#Sta/Elev= 21
     9.6  786.66    19.3  781.47    28.9  776.35    38.6  771.47    48.2  766.61
    57.9  761.83    67.5  757.24    77.2  754.01    86.8  752.67      89  752.64
    96.5  752.52     104  753.47   106.1  753.74   115.8  755.33   125.4  756.65
   135.1  757.63   144.7  758.38   154.4  758.96   164.0  759.22   173.7  759.44
   183.3  759.72
#Mann= 3 , 0 , 0
       0     0.1       0      89   0.045       0     104     0.1       0
Bank Sta=      89,     104
Exp/Cntr=0.3,0.1

Type RM Length L Ch R = 1 ,393.1,390.4,393.1,395.8
XS GIS Cut Line= 2
     1595150.369      364687.714     1595134.361      364975.857
#Sta/Elev= 27
    10.0  777.48    19.9  773.64    29.9  770.21    39.8  767.27    49.8  764.71
    59.7  762.36    69.7  760.16    79.6  758.19    89.6  756.47   109.5  753.38
   119.4  751.95   129.4  750.80   139.3  749.95   149.3  749.30   161.7  748.79
   169.2  748.62   176.7  748.83   179.1  748.90   189.1  749.91   209.0  752.83
   228.9  755.21   238.8  756.65   248.8  758.30   258.7  760.13   268.7  762.66
   278.6  766.71   288.6  772.22
#Mann= 3 , 0 , 0
       0     0.1       0   161.7   0.045       0   176.7     0.1       0
Bank Sta=   161.7,   176.7
Exp/Cntr=0.3,0.1